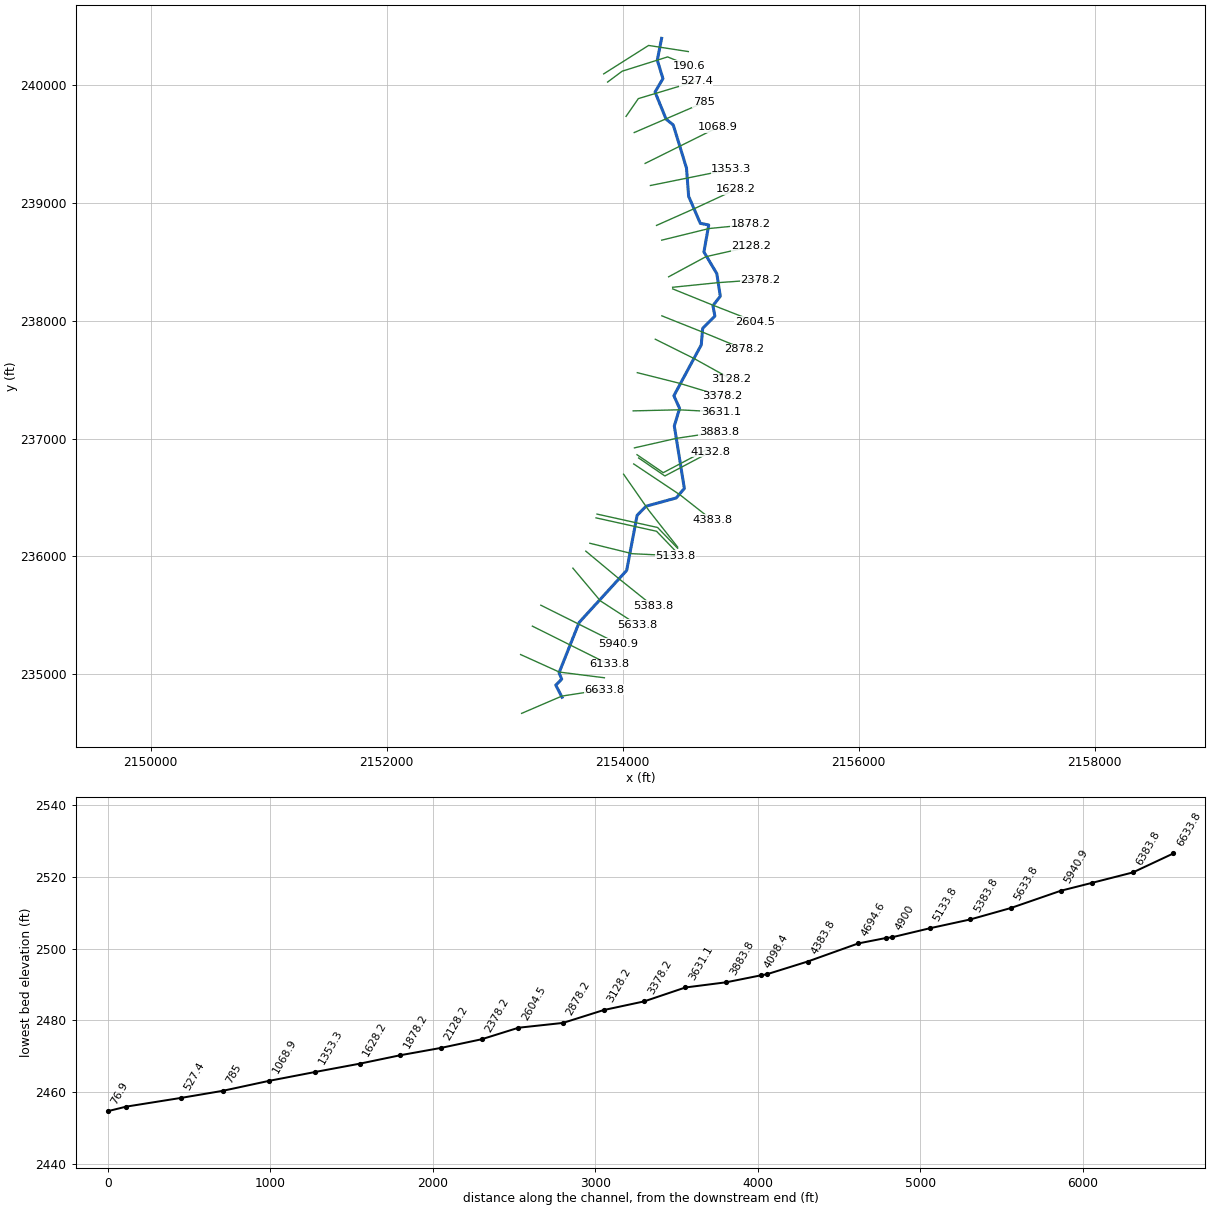
--- LLAURELCK.prj (project) ---

Proj Title=LLAURELCK
Current Plan=p01
Default Exp/Contr=0,0
English Units
Geom File=g01
Flow File=f01
Plan File=p01
BEGIN DESCRIPTION:
END DESCRIPTION:
DSS Export Rating Curves= 0
DSS Export Rating Curve Sorted= 0
DSS Export Volume Flow Curves= 0
DXF OffsetX= 0
DXF OffsetY= 0
DXF ScaleX= 0
DXF ScaleY= 0

--- LLAURELCK.p01 (plan) ---

Plan Title=Floodplain
Program Version=4.00
Geom File=g01
Flow File=f01
K Sum by GR=0
Std Step Tol=0.01
Critical Tol=0.01
Num of Std Step Trials=20
Max Error Tol=0.3
Flow Tol Ratio=0.001
Split Flow NTrial=30
Split Flow Tol=0.02
Split Flow Ratio=0.02
Log Output Level=0
Friction Slope Method=1
Unsteady Friction Slope Method=2
Unsteady Bridges Friction Slope Method=1
Global Log Level=0
CheckData=False
Run HTab=0
Run UNet=0
Run PostProcess=0
UNET Theta=0
UNET Theta Warmup=0
UNET ZTol=0
UNET ZSATol=0
UNET MxIter=0
UNET MaxInSteps=0
UNET DtIC=0
UNET DtMin=0
UNET MaxCRTS=0
UNET WFStab=0
UNET SFStab=0
UNET WFX=0
UNET SFX=0
UNET DSS MLevel=0
UNET DZMax Abort=0
UNET Convert EG Bridges=0
UNET Use Existing IB Tables=0
UNET Froude Limit=0
UNET Froude Power=0
Write IC File=0
Echo Input=False
Echo Output=False
Write Detailed=0

--- LLAURELCK.f01 (steady flow) ---

Flow Title=2010 USGS WV Regression Equation
Program Version=4.00
Number of Profiles=1
Profile Names=P100yr
River Rch & RM=LLAURELCK,Main      ,6633.8
509.4001
River Rch & RM=LLAURELCK,Main      ,5940.9
547.4060
River Rch & RM=LLAURELCK,Main      ,3883.8
596.3181
River Rch & RM=LLAURELCK,Main      ,2378.2
662.1622
River Rch & RM=LLAURELCK,Main      ,527.4
719.5825
River Rch & RM=LLAURELCK,Main      ,190.6
721.4946
Boundary for River Rch & Prof#=LLAURELCK,Main      ,1
Up Type=0
Dn Type=3
Dn Slope=0.008733

--- LLAURELCK.g01 (geometry) ---

Geom Title=LiDAR
Program Version=4.10

River Reach=LLAURELCK       ,Main
Reach XY= 30
     2153486.009      234804.212     2153432.623      234907.077
     2153482.971      234958.292     2153460.401      235012.111
      2153630.54      235439.195     2154033.318      235881.035
     2154121.859      236348.917      2154197.38      236426.174
     2154453.456      236496.486     2154522.033      236577.215
     2154436.963      237107.597     2154481.881      237256.315
     2154433.491      237364.542     2154665.262      237795.965
     2154677.415       237936.59     2154780.713      238040.757
      2154764.22      238129.299      2154826.72       238209.16
     2154797.206         238401.     2154687.832      238585.028
      2154728.63      238814.194     2154657.449      238828.083
     2154558.491       239057.25     2154540.262      239296.833
     2154428.283      239663.153     2154367.519      239712.632
     2154273.769      239942.667     2154340.609       240057.25
     2154292.866        240213.5     2154329.444      240398.879

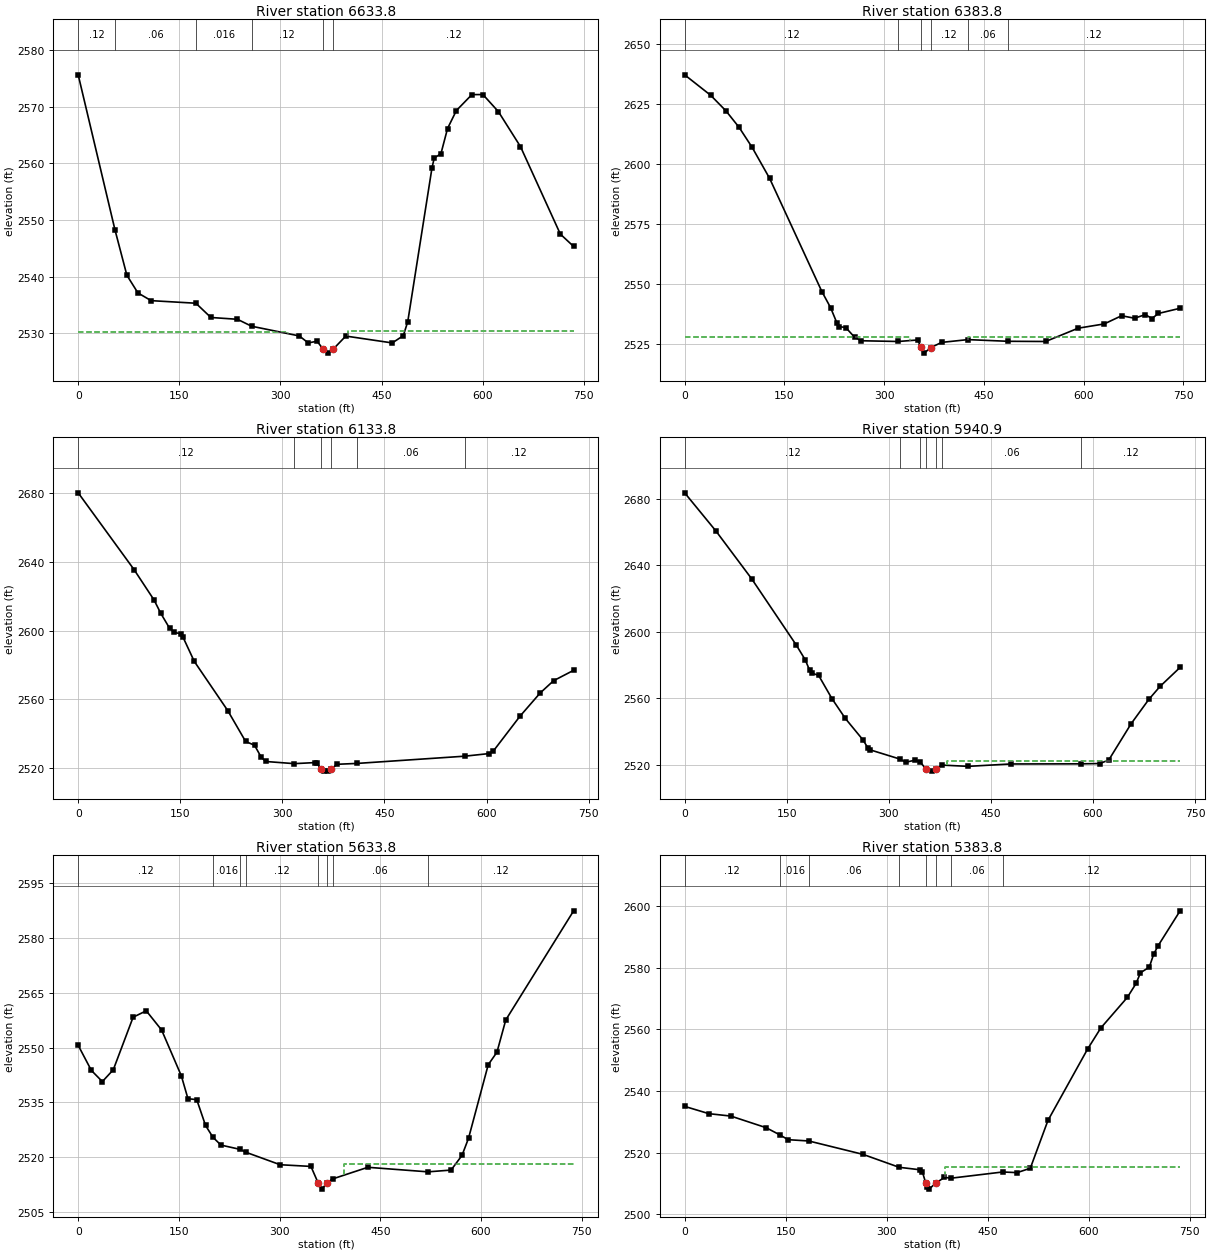
Type RM Length L Ch R = 1 ,6633.8  ,269.2,250,241.1
XS GIS Cut Line= 3
     2153143.271       234667.35     2153483.718      234813.946
      2153843.45      234870.029
#Sta/Elev= 30
       0 2575.62   54.45 2548.32    72.2 2540.26    88.6 2537.14   108.2 2535.78
  174.572535.323   196.8 2532.81   236.2 2532.49  257.132531.267     328 2529.55
   341.2 2528.32   354.3 2528.62   363.2 2527.24   370.7 2526.52   378.2 2527.22
   396.9 2529.53   465.8 2528.32   482.2  2529.6   488.8 2532.08   524.8 2559.26
   528.1 2560.94     538 2561.71   547.8 2566.15   560.9 2569.32   583.9 2572.13
   600.3 2572.14   623.2 2569.13     656 2562.95   715.1 2547.52   734.8 2545.34
#Mann= 6 ,-1 , 0
       0     .12       0   54.45     .06       0  174.57    .016       0
  257.13     .12       0   363.2    .045       0   378.2     .12       0
#XS Ineff= 2 , 0
          311.69 2530.26  400.41         2530.48
Permanent Ineff=
       F       F
Bank Sta=363.2,378.2
XS Rating Curve= 0 ,0
Exp/Cntr=0.3,0.1

Type RM Length L Ch R = 1 ,6383.8  ,250.3,250,241
XS GIS Cut Line= 3
     2153134.705      235166.788     2153462.807      235018.127
     2153844.527      234969.676
#Sta/Elev= 30
       0  2637.2    39.3 2628.63    62.2 2622.15    81.9 2615.29   101.5 2606.95
   127.7 2594.08   206.3 2546.89   219.4 2540.18   229.2 2533.63   232.5 2532.27
   242.3 2531.86   255.4 2527.88   265.2 2526.37  321.022526.064   350.4 2526.69
   355.42523.629   360.2 2521.21     370  2523.5   386.3 2525.68  425.85 2526.84
  486.152526.144   542.8 2526.06   591.7  2531.6   630.9 2533.38     657 2536.79
   676.5 2535.76   692.8 2537.27   702.6 2535.63   712.4 2537.74     745 2539.91
#Mann= 6 ,-1 , 0
       0     .12       0  321.02    .016       0   355.4    .045       0
     370     .12       0  425.85     .06       0  486.15     .12       0
#XS Ineff= 2 , 0
          339.09 2528.09  425.92         2527.81
Permanent Ineff=
       F       F
Bank Sta=355.4,370
XS Rating Curve= 0 ,0
Exp/Cntr=0.3,0.1

Type RM Length L Ch R = 1 ,6133.8  ,193,192.9,192.7
XS GIS Cut Line= 3
     2153234.457      235408.006     2153560.028       235245.22
       2153885.6      235082.434
#Sta/Elev= 30
       0 2680.12      82 2635.54   111.5  2617.8   121.3 2610.11   134.4 2601.32
     141 2599.01   150.8 2598.16   154.1 2596.14   170.5 2582.17   219.7 2553.55
     246 2535.59   259.1 2533.35   268.9 2526.45   275.5 2523.93  317.542522.667
   347.6 2523.28   350.9 2522.78   357.4 2519.59   360.7  2518.5   367.3 2518.32
  371.922519.625   380.4  2522.3  409.532522.791  568.04 2527.01   603.4 2528.51
     610 2529.98   649.3 2550.31   678.8 2563.73   698.5 2570.88     728 2576.93
#Mann= 6 ,-1 , 0
       0     .12       0  317.54    .016       0   357.4    .045       0
  371.92     .12       0  409.53     .06       0  568.04     .12       0
Bank Sta=357.4,371.92
XS Rating Curve= 0 ,0
Exp/Cntr=0.3,0.1

Type RM Length L Ch R = 1 ,5940.9  ,305.9,307.1,301.9
XS GIS Cut Line= 3
     2153305.637      235585.957     2153631.209      235423.171
      2153956.78      235260.386
#Sta/Elev= 30
       0 2683.48    45.9 2660.55    98.4 2631.81     164 2591.94   177.1 2583.12
   183.6 2576.81   186.9 2575.03   196.8 2573.72   216.4 2559.73   236.1 2547.79
   262.3 2534.75   268.9 2530.27   272.2 2528.95   316.6 2523.33   324.6 2521.46
   337.8 2522.62  345.67 2521.84   354.2 2517.55     364 2516.11  369.122517.555
  378.692519.732   416.5 2518.98   478.8 2520.41  582.86 2520.49     610 2520.68
   623.1 2522.74   655.9 2544.52   682.1 2559.27   698.5 2567.04     728 2578.49
#Mann= 7 ,-1 , 0
       0     .12       0   316.6    .016       0  345.67     .12       0
   354.2    .045       0  369.12     .12       0  378.69     .06       0
  582.86     .12       0
#XS Ineff= 2 , 0
                          385.43         2522.38
Permanent Ineff=
       F       F
Bank Sta=354.2,369.12
XS Rating Curve= 0 ,0
Exp/Cntr=0.3,0.1

Type RM Length L Ch R = 1 ,5633.8  ,245.7,250,247.3
XS GIS Cut Line= 3
      2153577.73      235900.314     2153810.964      235622.147
     2154125.757      235418.436
#Sta/Elev= 30
       0 2550.62    19.6 2543.77      36 2540.71    52.3 2543.95    81.8 2558.31
   101.4 2560.07   124.3 2554.81   153.7 2542.26   163.5 2536.03   176.6 2535.77
   189.7 2528.71  200.752525.483   212.6 2523.35  241.572522.156  249.472521.406
   300.9 2517.97   346.7 2517.51  357.632512.908     363  2511.3   370.5 2512.98
  378.862514.083   431.5 2517.27  521.092516.027   555.4 2516.51   571.7 2520.51
   581.5 2525.24   610.8 2545.33   623.8 2548.75   636.9 2557.56     738 2587.41
#Mann= 8 ,-1 , 0
       0     .12       0  200.75    .016       0  241.57     .06       0
  249.47     .12       0  357.63    .045       0   370.5     .12       0
  378.86     .06       0  521.09     .12       0
#XS Ineff= 2 , 0
                          395.68         2518.26
Permanent Ineff=
       F       F
Bank Sta=357.63,370.5
XS Rating Curve= 0 ,0
Exp/Cntr=0.3,0.1

Type RM Length L Ch R = 1 ,5383.8  ,239.3,250,263.7
XS GIS Cut Line= 3
     2153686.993      236044.838     2153965.596      235812.445
     2154256.441      235579.156
#Sta/Elev= 30
       0 2534.99      36 2532.62    68.6 2531.84   120.9 2528.07  141.052525.764
   153.6 2524.17  184.332523.749   264.8  2519.4   318.52515.203   349.7 2514.39
     353 2513.67   358.12509.997   359.5 2508.82   362.8 2508.11   372.6    2510
   385.7 2511.93  395.47 2511.66  472.332513.681   493.6 2513.47   513.2 2514.89
   539.4 2530.42   598.3 2553.62   617.9 2560.46   657.2 2570.37   670.2 2574.91
   676.8 2578.39   689.9 2580.23   696.4 2584.44   702.9 2587.15   735.6 2598.51
#Mann= 8 ,-1 , 0
       0     .12       0  141.05    .016       0  184.33     .06       0
   318.5     .12       0   358.1    .045       0   372.6     .12       0
  395.47     .06       0  472.33     .12       0
#XS Ineff= 2 , 0
                          385.99         2515.25
Permanent Ineff=
       F       F
Bank Sta=358.1,372.6
XS Rating Curve= 0 ,0
Exp/Cntr=0.3,0.1

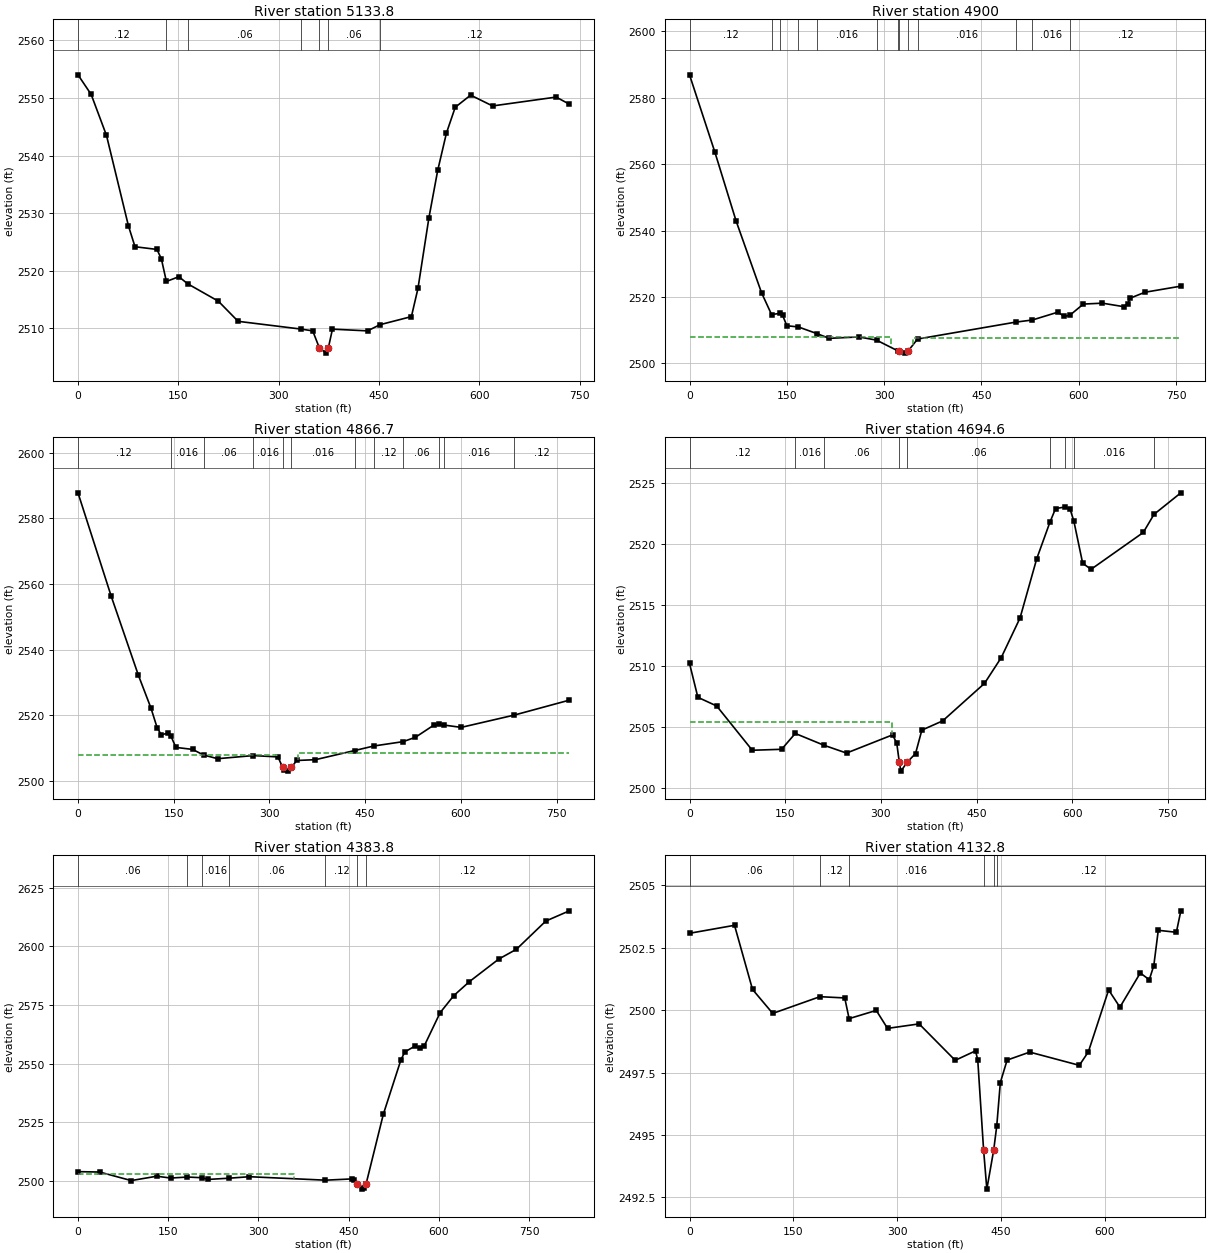
Type RM Length L Ch R = 1 ,5133.8  ,232.9,233.9,229.7
XS GIS Cut Line= 3
     2153721.624      236111.665     2154081.357      236023.034
     2154444.707      236005.639
#Sta/Elev= 30
       0 2554.03    19.7 2550.62    42.6 2543.49    75.4 2527.77    85.2 2524.14
     118 2523.67   124.6 2522.04  132.11  2518.1   150.8 2518.93  163.722517.711
   209.8 2514.67   239.3 2511.17  333.652509.816   350.8 2509.51   360.6 2506.59
   370.5 2505.64  374.262506.599   380.3 2509.81   432.8 2509.51  451.182510.579
   498.3 2511.99   508.1 2516.89   524.5  2529.2   537.6 2537.41   550.7 2543.92
   563.8 2548.39   586.8  2550.5   619.6 2548.62   714.6 2550.16   734.3 2548.93
#Mann= 7 ,-1 , 0
       0     .12       0  132.11    .016       0  163.72     .06       0
  333.65     .12       0   360.6    .045       0  374.26     .06       0
  451.18     .12       0
Bank Sta=360.6,374.26
XS Rating Curve= 0 ,0
Exp/Cntr=0.3,0.1

Type RM Length L Ch R = 1 ,4900    ,33.4,33.3,33.4
XS GIS Cut Line= 3
     2153773.598      236327.288     2154286.619      236213.573
      2154447.21      236046.038
#Sta/Elev= 30
       0 2586.84    39.2 2563.52    71.8 2542.88     111  2521.3  126.522514.708
  139.83 2515.09   143.6 2514.44   150.1 2511.35  167.76 2510.99  196.012509.011
   215.4 2507.56   261.1 2507.98  288.292507.024  321.362503.776   322.7 2503.67
   332.9 2503.11  336.812503.699  351.61 2507.35  502.882512.439  528.582513.076
     568 2515.44   577.8 2514.14   586.52514.523   607.2 2517.87   636.6 2518.14
   669.3 2517.09   675.8 2518.02   679.1 2519.62     702 2521.42   757.5 2523.26
#Mann= 13 ,-1 , 0
       0     .12       0  126.52     .06       0  139.83    .016       0
  167.76     .06       0  196.01    .016       0  288.29     .06       0
  321.36     .12       0   322.7    .045       0  336.81     .12       0
  351.61    .016       0  502.88     .06       0  528.58    .016       0
   586.5     .12       0
#XS Ineff= 2 , 0
          310.13 2507.92  344.77         2507.76
Permanent Ineff=
       F       F
Bank Sta=322.7,336.81
XS Rating Curve= 0 ,0
Exp/Cntr=0.3,0.1

Type RM Length L Ch R = 1 ,4866.7  ,189.1,172.1,155.5
XS GIS Cut Line= 3
     2153782.279      236359.406       2154295.3      236245.691
     2154464.571      236069.476
#Sta/Elev= 30
       0 2587.76    52.2 2556.17    94.6 2532.19   114.2 2522.24     124 2516.19
   130.6 2513.98   140.3 2514.54  145.272513.783   153.4 2510.18   179.5 2509.57
  196.662507.873   218.7 2506.74  274.882507.691   313.3 2507.28  320.622504.112
   323.1 2503.21   329.6 2502.95   334.4  2504.1   342.7 2506.19   372.1 2506.44
  433.482509.227  463.742510.618  509.472511.937   528.7 2513.27     558 2517.03
  566.382517.172  573.12    2517   600.4 2516.28  683.522520.027   769.8 2524.58
#Mann= 12 ,-1 , 0
       0     .12       0  145.27    .016       0  196.66     .06       0
  274.88    .016       0  320.62    .045       0   334.4    .016       0
  433.48     .06       0  463.74     .12       0  509.47     .06       0
  566.38     .12       0  573.12    .016       0  683.52     .12       0
#XS Ineff= 2 , 0
          311.97 2508.01  344.84         2508.39
Permanent Ineff=
       F       F
Bank Sta=320.62,334.4
XS Rating Curve= 0 ,0
Exp/Cntr=0.3,0.1

Type RM Length L Ch R = 1 ,4694.6  ,301,310.8,316.7
XS GIS Cut Line= 3
       2154007.2      236698.182     2154220.662      236391.073
     2154465.258      236079.352
#Sta/Elev= 30
       0 2510.25    13.1 2507.47    42.6 2506.76    98.4 2503.13   144.4 2503.21
  165.772504.508  210.742503.541   246.1  2502.9   318.2 2504.39   324.8 2503.73
  328.912502.137   331.4 2501.42   341.2 2502.15   354.3 2502.86   364.2 2504.78
   396.9 2505.54   462.4 2508.61   488.6 2510.72   518.1 2513.97   544.3 2518.83
  564.932521.817   573.8 2522.94  588.672523.067   596.7 2522.87  602.472521.913
   616.3 2518.46   629.4 2517.96   711.3 2520.98  728.132522.467   770.2 2524.23
#Mann= 9 ,-1 , 0
       0     .12       0  165.77    .016       0  210.74     .06       0
  328.91    .045       0   341.2     .06       0  564.93     .12       0
  588.67     .06       0  602.47    .016       0  728.13     .12       0
#XS Ineff= 2 , 0
          317.03 2505.41
Permanent Ineff=
       F       F
Bank Sta=328.91,341.2
XS Rating Curve= 0 ,0
Exp/Cntr=0.3,0.1

Type RM Length L Ch R = 1 ,4383.8  ,224.6,251,277.4
XS GIS Cut Line= 3
     2154093.226       236785.06      2154485.44      236522.891
     2154756.419       236309.39
#Sta/Elev= 30
       0 2503.84      36 2503.68    88.5 2500.03     131 2501.89     154 2501.11
     182 2501.54  206.052501.249   216.2 2500.52  251.23 2501.05     285 2501.68
  411.44  2500.2   455.4 2500.74   458.7 2500.44   464.3  2498.4   471.8 2496.38
     475  2496.7  478.722498.365   507.6 2528.34   536.9 2551.61   543.4 2554.97
   559.6 2557.36   569.4 2556.72   575.9 2557.67     602  2571.7   624.7 2578.99
   650.8 2584.99   699.6 2594.62   728.9 2598.79   777.7 2610.83   816.8  2615.2
#Mann= 7 ,-1 , 0
       0     .06       0     182     .12       0  206.05    .016       0
  251.23     .06       0  411.44     .12       0   464.3    .045       0
  478.72     .12       0
#XS Ineff= 2 , 0
          359.15 2503.03
Permanent Ineff=
       F       F
Bank Sta=464.3,478.72
XS Rating Curve= 0 ,0
Exp/Cntr=0.3,0.1

Type RM Length L Ch R = 1 ,4132.8  ,35.3,34.4,34.2
XS GIS Cut Line= 3
      2154134.71      236835.969     2154356.932      236683.191
     2154745.821       236888.92
#Sta/Elev= 30
       0 2503.08      65  2503.4      91 2500.83   120.2 2499.87  188.34 2500.54
   224.2 2500.49  230.482499.661   269.7 2499.99     286 2499.27   331.6 2499.45
   383.7 2497.99   413.1 2498.37   416.3    2498  424.752494.387   429.4 2492.83
   439.3 2494.39  443.732495.365   448.9  2497.1   458.7    2498   491.3 2498.32
     563 2497.79     576 2498.33   605.3 2500.81   621.6 2500.12     651 2501.49
     664 2501.22   670.5 2501.78     677  2503.2   703.1 2503.12   709.6 2503.98
#Mann= 6 ,-1 , 0
       0     .06       0  188.34     .12       0  230.48    .016       0
  424.75    .045       0   439.3    .016       0  443.73     .12       0
Bank Sta=424.75,439.3
XS Rating Curve= 0 ,0
Exp/Cntr=0.3,0.1

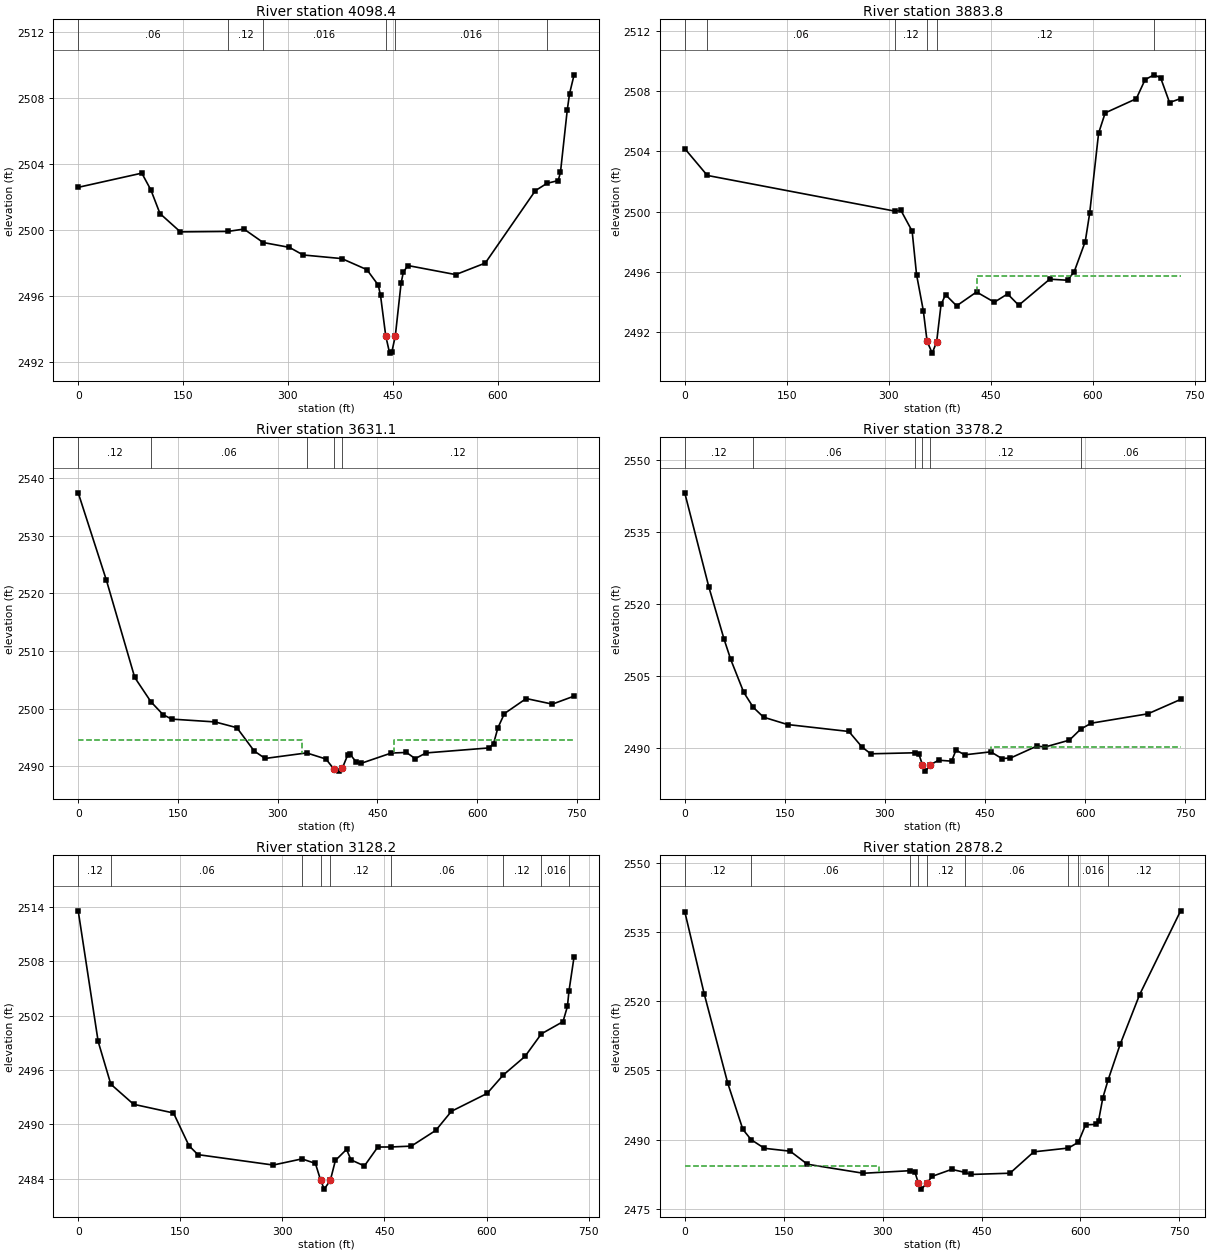
Type RM Length L Ch R = 1 ,4098.4  ,221.4,214.6,206.5
XS GIS Cut Line= 3
     2154120.821      236863.746     2154343.043      236710.969
     2154731.932      236916.698
#Sta/Elev= 30
       0  2502.6      91 2503.46     104 2502.44     117 2501.01   146.2  2499.9
  214.142499.927   237.2 2500.07  264.682499.255   302.3 2498.96   321.8  2498.5
   377.2 2498.28   413.1 2497.61   429.4 2496.67   432.6 2496.05  440.042493.601
   445.6 2492.55   448.9 2492.64  453.812493.605     462 2496.78   465.2 2497.45
   471.7 2497.86   540.2 2497.31   582.5 2498.01   654.2  2502.4  670.792502.842
   686.8 2503.01   690.1 2503.51   699.8 2507.28   703.1 2508.28   709.6 2509.42
#Mann= 6 ,-1 , 0
       0     .06       0  214.14     .12       0  264.68    .016       0
  440.04    .045       0  453.81    .016       0  670.79     .12       0
Bank Sta=440.04,453.81
XS Rating Curve= 0 ,0
Exp/Cntr=0.3,0.1

Type RM Length L Ch R = 1 ,3883.8  ,257,252.7,247.8
XS GIS Cut Line= 3
     2154098.974      236921.673     2154453.714      237002.296
     2154814.845      237056.723
#Sta/Elev= 30
       0 2504.18   33.182502.398  308.442500.031   317.9 2500.07   334.3  2498.7
   340.8 2495.81   350.7 2493.43   356.3 2491.38   363.8  2490.6   370.3 2491.34
   376.8 2493.83   383.4 2494.48   399.7 2493.74     429 2494.66   455.1 2493.98
   474.6 2494.53     491 2493.78   536.6 2495.51   562.7 2495.44   572.5    2496
   588.8 2498.01   595.3 2499.89   608.4  2505.2   618.1 2506.55   663.8 2507.49
   676.8 2508.76  690.022509.078   699.6 2508.88   712.7 2507.24     729  2507.5
#Mann= 6 ,-1 , 0
       0     .12       0   33.18     .06       0  308.44     .12       0
   356.3    .045       0   370.3     .12       0  690.02    .016       0
#XS Ineff= 2 , 0
                          429.31         2495.71
Permanent Ineff=
       F       F
Bank Sta=356.3,370.3
XS Rating Curve= 0 ,0
Exp/Cntr=0.3,0.1

Type RM Length L Ch R = 1 ,3631.1  ,257.6,253,245.9
XS GIS Cut Line= 3
     2154088.284      237235.797     2154473.815      237244.807
     2154833.548      237226.819
#Sta/Elev= 30
       0 2537.45    42.5 2522.24      85  2505.4  109.432501.169   127.5 2498.96
   140.5 2498.17   205.9 2497.68   238.6 2496.68   264.7 2492.63   281.1 2491.34
  343.592492.301   372.6 2491.24  383.962489.583   392.2 2489.14  397.08 2489.62
   405.3 2491.93   408.6 2492.09   418.4 2490.69   424.9 2490.47   470.8 2492.28
   493.7 2492.38   506.8 2491.31   523.2  2492.3   618.1 2493.17   624.7 2493.93
   631.2 2496.65     641 2499.13   673.8 2501.74   713.1 2500.77   745.8 2502.16
#Mann= 5 ,-1 , 0
       0     .12       0  109.43     .06       0  343.59     .12       0
  383.96    .045       0  397.08     .12       0
#XS Ineff= 2 , 0
          336.84 2494.59  475.54         2494.59
Permanent Ineff=
       F       F
Bank Sta=383.96,397.08
XS Rating Curve= 0 ,0
Exp/Cntr=0.3,0.1

Type RM Length L Ch R = 1 ,3378.2  ,254.5,250,244.6
XS GIS Cut Line= 3
     2154123.782      237560.104     2154473.601       237472.03
     2154839.676      237361.143
#Sta/Elev= 30
       0  2543.1    36.1 2523.55      59 2512.66    68.9 2508.48    88.5 2501.62
  102.672498.531   118.1 2496.48   154.1 2494.95     246 2493.51   265.6 2490.29
   278.8 2488.87  344.472489.079   350.9 2488.81  356.172486.618   360.7 2485.27
   368.2 2486.58   380.4 2487.54     400 2487.34   406.5 2489.64   419.6 2488.66
   458.8 2489.28   475.2 2487.89   488.2 2487.99   527.5 2490.46   540.5  2490.3
   576.5 2491.71   593.52494.001   609.2 2495.23   694.2 2497.18   743.2 2500.17
#Mann= 6 ,-1 , 0
       0     .12       0  102.67     .06       0  344.47     .12       0
  356.17    .045       0   368.2     .12       0   593.5     .06       0
#XS Ineff= 2 , 0
                          459.71         2490.25
Permanent Ineff=
       F       F
Bank Sta=356.17,368.2
XS Rating Curve= 0 ,0
Exp/Cntr=0.3,0.1

Type RM Length L Ch R = 1 ,3128.2  ,247.6,250,252.2
XS GIS Cut Line= 3
     2154275.664       237844.22     2154602.098      237681.403
     2154920.171      237504.697
#Sta/Elev= 30
       0 2513.58    29.3 2499.15   47.912494.432    81.4 2492.21     140 2491.25
   162.8 2487.63   175.9 2486.65   286.6  2485.5  328.71 2486.18   348.5 2485.68
  356.292483.801   361.5 2482.84  370.442483.809   377.9 2486.01   394.3 2487.23
   400.8 2486.07   420.5  2485.4   440.2 2487.49  459.152487.496   489.4 2487.59
   525.4 2489.33   548.4 2491.44   600.8 2493.41  624.372495.433   656.5  2497.5
   680.52499.991   712.3 2501.34   718.8 2503.02  721.062504.712   728.6 2508.52
#Mann= 9 ,-1 , 0
       0     .12       0   47.91     .06       0  328.71     .12       0
  356.29    .045       0  370.44     .12       0  459.15     .06       0
  624.37     .12       0   680.5    .016       0  721.06     .12       0
Bank Sta=356.29,370.44
XS Rating Curve= 0 ,0
Exp/Cntr=0.3,0.1

Type RM Length L Ch R = 1 ,2878.2  ,273,273.7,273.5
XS GIS Cut Line= 3
     2154331.259      238042.778      2154664.49      237909.487
     2155027.678       237759.61
#Sta/Elev= 30
       0 2539.43    29.4 2521.65    65.2 2502.23    88.1 2492.21  100.732489.974
   120.7 2488.11   159.9 2487.48     186 2484.65   270.8  2482.7  341.592483.255
   349.1  2482.9  354.222480.552   358.9 2479.26  367.242480.613   375.3 2482.04
   404.7 2483.54  424.592482.897   434.2 2482.44   493.1 2482.71   529.2 2487.34
   581.72488.166  596.742489.419   607.7  2493.2   624.1 2493.29   627.4 2494.09
   633.9 2499.07  641.862502.927   660.1 2510.63   689.6  2521.4   751.8 2539.58
#Mann= 9 ,-1 , 0
       0     .12       0  100.73     .06       0  341.59     .12       0
  354.22    .045       0  367.24     .12       0  424.59     .06       0
   581.7     .12       0  596.74    .016       0  641.86     .12       0
#XS Ineff= 2 , 0
          295.05 2484.37
Permanent Ineff=
       F       F
Bank Sta=354.22,367.24
XS Rating Curve= 0 ,0
Exp/Cntr=0.3,0.1

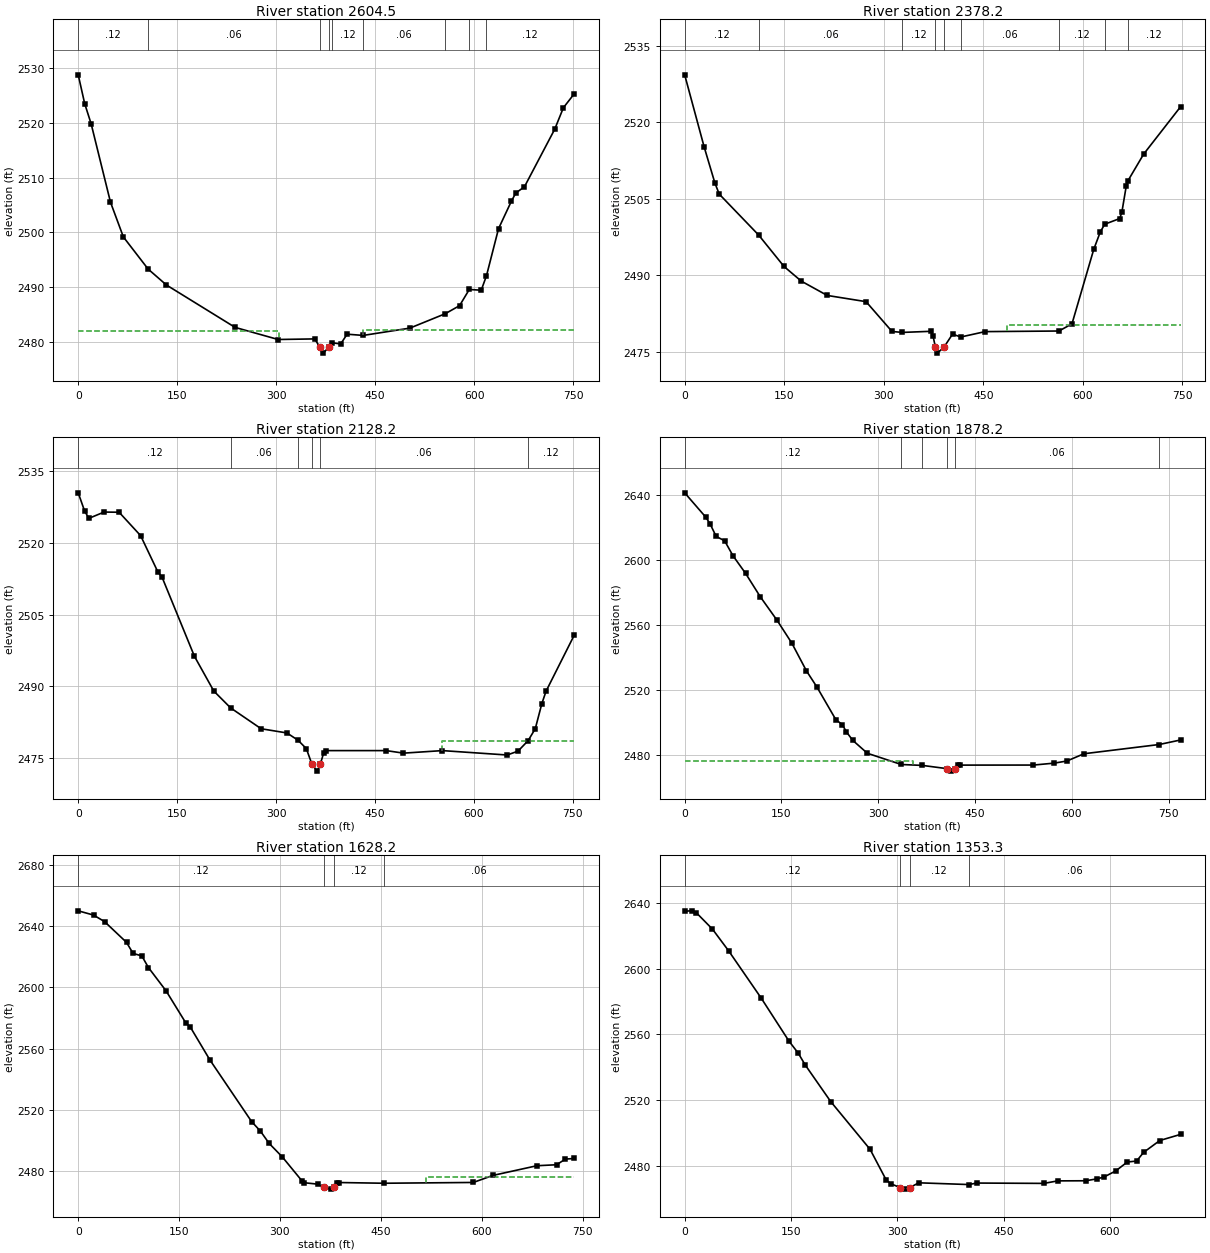
Type RM Length L Ch R = 1 ,2604.5  ,213.6,226.3,235.4
XS GIS Cut Line= 3
     2154423.202      238271.585     2154761.375      238134.434
     2155121.297      237993.261
#Sta/Elev= 30
       0 2528.79     9.8 2523.53    19.6 2519.83    48.9 2505.51    68.4 2499.16
  105.992493.277   133.6 2490.38   237.8 2482.62     303 2480.41   358.4 2480.52
  365.672479.113   371.5 2477.92  380.022479.084  384.422479.821   397.7  2479.6
   407.5 2481.38  431.872481.157   502.5 2482.49  556.092485.118   577.9  2486.6
  592.582489.556   610.7 2489.42  618.652492.063   636.9 2500.67   656.5 2505.72
   663.1 2507.19   676.2 2508.33   722.1 2518.86   735.2 2522.78   751.5  2525.3
#Mann= 9 ,-1 , 0
       0     .12       0  105.99     .06       0  365.67    .045       0
  380.02     .06       0  384.42     .12       0  431.87     .06       0
  556.09     .12       0  592.58    .016       0  618.65     .12       0
#XS Ineff= 2 , 0
          304.57 2481.95  431.14         2482.13
Permanent Ineff=
       F       F
Bank Sta=365.67,380.02
XS Rating Curve= 0 ,0
Exp/Cntr=0.3,0.1

Type RM Length L Ch R = 1 ,2378.2  ,240.9,250,252.8
XS GIS Cut Line= 3
      2154422.65      238285.244     2154804.616      238324.145
     2155167.029      238350.018
#Sta/Elev= 30
       0 2529.32    29.3 2515.19    45.6 2508.06    52.1 2505.91  111.432497.884
   149.7 2491.71   175.7 2488.84   214.8 2486.03   273.3 2484.81   312.4 2478.96
  327.872478.774   370.9 2478.99   374.2 2478.08  377.812475.884   380.7 2474.71
   390.5 2475.84   403.6 2478.43  416.162477.876   452.7 2478.93     564 2479.05
   583.6 2480.46   616.4 2495.07   626.2 2498.47  632.872500.004   655.6 2501.12
   658.9 2502.46   665.4 2507.52  667.95 2508.54   691.6 2513.76   747.3 2523.07
#Mann= 9 ,-1 , 0
       0     .12       0  111.43     .06       0  327.87     .12       0
  377.81    .045       0   390.5     .12       0  416.16     .06       0
     564     .12       0  632.87    .016       0  667.95     .12       0
#XS Ineff= 2 , 0
                          485.93         2480.28
Permanent Ineff=
       F       F
Bank Sta=377.81,390.5
XS Rating Curve= 0 ,0
Exp/Cntr=0.3,0.1

Type RM Length L Ch R = 1 ,2128.2  ,255.3,250,246.8
XS GIS Cut Line= 3
     2154389.119      238374.298      2154704.79      238544.959
     2155088.106      238631.483
#Sta/Elev= 30
       0 2530.48     9.8 2526.63    16.3 2525.15    39.2 2526.46      62 2526.42
    94.6 2521.53   120.7 2513.96   127.2 2512.81   176.2  2496.3   205.5 2489.05
  231.052485.517   277.3 2481.16   316.4 2480.28  333.122478.771   345.8 2477.01
  354.032473.854   362.1  2472.3  367.152473.815     372 2476.06   375.2 2476.59
   466.9 2476.59   493.1 2476.06   552.1 2476.59   650.3 2475.67   666.7 2476.48
  682.012478.671   692.9 2481.18   702.7 2486.36   709.2 2489.01   751.8 2500.69
#Mann= 6 ,-1 , 0
       0     .12       0  231.05     .06       0  333.12     .12       0
  354.03    .045       0  367.15     .06       0  682.01     .12       0
#XS Ineff= 2 , 0
                          551.68         2478.69
Permanent Ineff=
       F       F
Bank Sta=354.03,367.15
XS Rating Curve= 0 ,0
Exp/Cntr=0.3,0.1

Type RM Length L Ch R = 1 ,1878.2  ,242.3,250,257.2
XS GIS Cut Line= 3
     2154330.336      238685.154     2154731.823         238784.
     2155085.329      238819.347
#Sta/Elev= 30
       0 2641.32    32.6  2626.4    39.1 2622.44    48.8 2614.52    61.9 2611.84
    74.9 2602.63    94.4 2591.81   117.2 2577.43   143.2 2562.97     166 2548.99
   188.8 2531.84   205.1 2521.88   234.4 2501.83   244.2 2498.92   250.7 2494.39
   260.5 2489.17   283.2 2481.23  335.772474.334  368.412473.776     406 2471.82
   413.5 2470.26  419.262471.767   423.2 2473.74   426.5 2473.96   540.6 2473.99
   573.2 2475.19   592.7 2476.51   618.8 2480.94  735.492486.616   768.7 2489.42
#Mann= 6 ,-1 , 0
       0     .12       0  335.77     .06       0  368.41     .12       0
     406    .045       0  419.26     .06       0  735.49     .12       0
#XS Ineff= 2 , 0
           353.5 2476.51
Permanent Ineff=
       F       F
Bank Sta=406,419.26
XS Rating Curve= 0 ,0
Exp/Cntr=0.3,0.1

Type RM Length L Ch R = 1 ,1628.2  ,279.8,274.8,268.8
XS GIS Cut Line= 3
     2154286.153      238810.456     2154629.049      238963.136
     2154957.456      239115.618
#Sta/Elev= 30
       0 2650.23    22.8 2647.45    39.2 2643.15    71.8 2629.57    81.6 2622.34
    94.6 2620.67   104.4 2613.06   130.6 2597.82   159.9 2576.85   166.5  2574.2
   195.8 2552.54   257.8 2512.16   270.9 2505.91     284 2497.81   303.5 2488.98
   332.9  2473.2   336.2 2472.08   355.8 2471.18   365.6    2469   375.4  2467.9
  380.642469.069   385.1 2471.67   388.4 2472.22  454.822471.753   587.4 2472.27
   616.7 2476.89     682 2483.23   711.3 2483.87   724.4 2487.58   737.4 2487.98
#Mann= 4 ,-1 , 0
       0     .12       0   365.6    .045       0  380.64     .12       0
  454.82     .06       0
#XS Ineff= 2 , 0
                          517.26         2475.91
Permanent Ineff=
       F       F
Bank Sta=365.6,380.64
XS Rating Curve= 0 ,0
Exp/Cntr=0.3,0.1

Type RM Length L Ch R = 1 ,1353.3  ,278,284.4,289.7
XS GIS Cut Line= 2
     2154234.666      239149.291      2154920.43       239288.18
#Sta/Elev= 30
       0 2635.29     9.8  2635.5    16.4 2634.35    39.2 2624.32    62.1 2611.02
   107.9 2582.25   147.1 2555.98   160.2  2548.6     170 2541.43     206 2519.06
   261.6 2489.86   284.4 2471.09     291 2468.84   304.2 2466.48   310.6 2465.58
  317.682466.501   330.2 2469.44  400.982468.371     412 2469.29   506.8 2469.08
   526.4 2470.62   565.6 2470.68     582 2471.87   591.8 2473.01   608.1 2476.69
   624.5 2482.14   637.6 2482.72   647.4 2487.99   670.3 2495.26   699.7 2499.01
#Mann= 4 ,-1 , 0
       0     .12       0   304.2    .045       0  317.68     .12       0
  400.98     .06       0
Bank Sta=304.2,317.68
XS Rating Curve= 0 ,0
Exp/Cntr=0.3,0.1

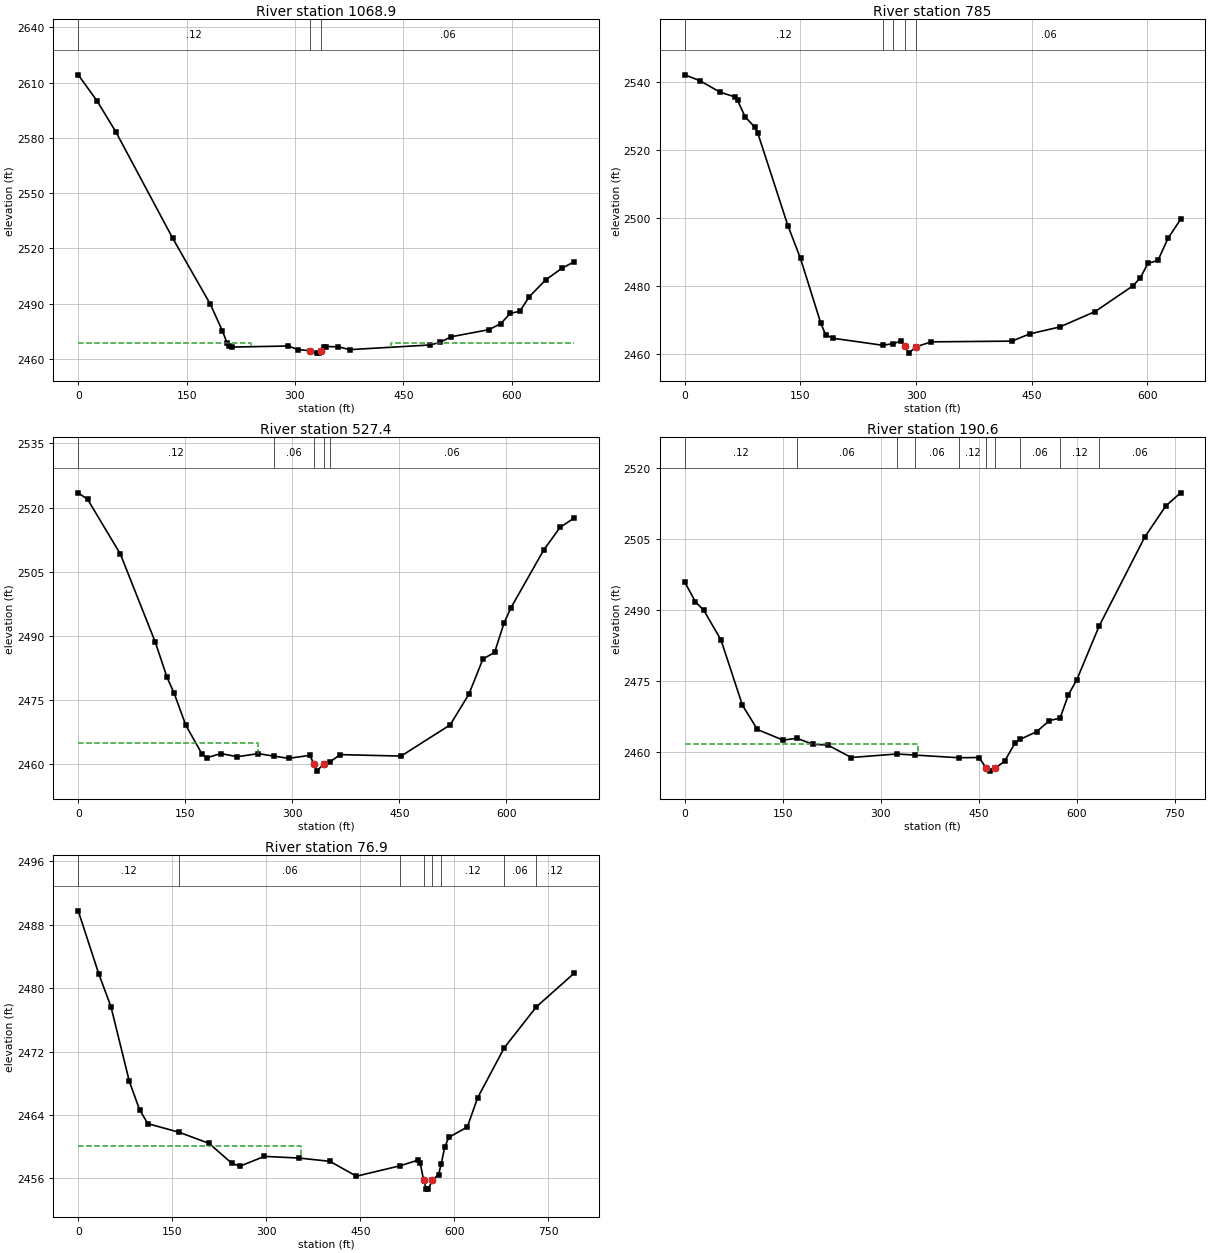
Type RM Length L Ch R = 1 ,1068.9  ,283.5,283.9,281.8
XS GIS Cut Line= 2
     2154189.527      239336.791     2154804.111      239642.347
#Sta/Elev= 30
       0 2614.24    26.2    2600    52.3 2583.11   130.7 2525.55     183 2489.58
   199.4 2475.32   205.9 2468.77   209.2 2466.96   212.4 2466.39   290.9 2466.97
     304 2465.01   320.7 2464.43   330.1  2463.1   333.4 2463.24  335.372464.422
   339.9 2466.51   343.2 2466.68   359.5 2466.55   375.9    2465     487 2467.52
   500.1 2468.89   516.4    2472   568.7 2475.87     585 2479.17   598.1 2484.74
   611.2 2485.79   624.2  2493.7   647.1 2502.93     670 2509.32   686.4 2512.68
#Mann= 3 ,-1 , 0
       0     .12       0   320.7    .045       0  335.37     .06       0
#XS Ineff= 2 , 0
          239.36 2468.49  433.45         2468.57
Permanent Ineff=
       F       F
Bank Sta=320.7,335.37
XS Rating Curve= 0 ,0
Exp/Cntr=0.3,0.1

Type RM Length L Ch R = 1 ,785     ,259.6,257.6,255.2
XS GIS Cut Line= 2
     2154097.513      239598.944     2154687.791      239854.152
#Sta/Elev= 30
       0 2542.02    19.6 2540.32    45.7 2536.94    65.3 2535.52    68.6 2534.53
    78.4 2529.66    91.4 2526.56    94.7 2524.98   133.8 2497.77   150.2 2488.11
   176.3 2469.25   182.8 2465.67   192.6 2464.69  256.842462.632  269.572463.098
   280.7 2463.83   285.3 2462.43   290.5 2460.33   300.3 2462.22   319.9 2463.64
   424.4 2463.85   447.2 2465.96   486.4 2468.01   532.1 2472.52   581.1 2480.06
   590.9 2482.41   600.6 2486.68   613.7 2487.54   626.8 2494.06   643.1 2499.61
#Mann= 5 ,-1 , 0
       0     .12       0  256.84     .06       0  269.57     .12       0
   285.3    .045       0   300.3     .06       0
Bank Sta=285.3,300.3
XS Rating Curve= 0 ,0
Exp/Cntr=0.3,0.1

Type RM Length L Ch R = 1 ,527.4   ,338,336.9,335.3
XS GIS Cut Line= 3
     2154028.069      239736.097     2154132.236      239887.138
     2154621.819      240034.708
#Sta/Elev= 30
       0 2523.45    13.1 2521.94      59 2509.15   108.1 2488.46   124.5 2480.26
   134.3 2476.61   150.7  2469.1   173.6  2462.3   180.2 2461.48   199.9 2462.46
   222.8 2461.72   252.3 2462.44  273.782461.864   294.9 2461.34   324.4 2462.04
  330.112460.117   334.3 2458.35   344.1 2460.06  352.312460.451     367 2462.21
   452.3 2461.87   521.1 2469.17   547.3 2476.33     567 2484.58   583.4 2486.13
   596.5 2492.98   606.3 2496.57   652.2 2510.09   675.2 2515.39   694.8 2517.55
#Mann= 5 ,-1 , 0
       0     .12       0  273.78     .06       0  330.11    .045       0
   344.1     .12       0  352.31     .06       0
#XS Ineff= 2 , 0
          252.12    2465
Permanent Ineff=
       F       F
Bank Sta=330.11,344.1
XS Rating Curve= 0 ,0
Exp/Cntr=0.3,0.1

Type RM Length L Ch R = 1 ,190.6   ,123.7,113.6,102.9
XS GIS Cut Line= 4
     2153871.819      240027.763     2153995.083      240119.777
       2154380.5      240241.305     2154566.263      240164.916
#Sta/Elev= 30
       0 2495.89    16.4 2491.72    29.4 2489.89    55.6 2483.62    88.4 2469.84
   111.3 2464.72   150.6 2462.47  171.56 2462.87   196.2 2461.58     219 2461.43
   254.8  2458.8  324.712459.543  352.472459.314  418.962458.751   450.4  2458.8
   461.52456.551   466.7 2455.92  475.152456.539   489.5 2458.02   505.8 2461.94
  513.34 2462.64   538.4 2464.25   557.9 2466.59  574.34 2467.13   587.1 2472.05
   600.1 2475.28  633.962486.528   703.7 2505.33   736.1 2511.97   758.8 2514.74
#Mann= 10 ,-1 , 0
       0     .12       0  171.56     .06       0  324.71     .12       0
  352.47     .06       0  418.96     .12       0   461.5    .045       0
  475.15     .12       0  513.34     .06       0  574.34     .12       0
  633.96     .06       0
#XS Ineff= 2 , 0
          357.48 2461.71
Permanent Ineff=
       F       F
Bank Sta=461.5,475.15
XS Rating Curve= 0 ,0
Exp/Cntr=0.3,0.1

Type RM Length L Ch R = 1 ,76.9    ,75,76.9,78.4
XS GIS Cut Line= 3
     2153838.833      240097.208     2154219.041      240338.527
     2154555.847      240286.444
#Sta/Elev= 30
       0 2489.75    32.6 2481.84    52.2 2477.66    81.6 2468.22    97.9 2464.66
     111  2462.9  161.452461.801   208.8 2460.41   244.7 2457.92   257.8 2457.53
     297 2458.77   352.4 2458.56   401.4 2458.15   443.8 2456.27  513.892457.594
   542.1  2458.3   545.4 2457.99   550.92455.794   555.2 2454.64   558.5 2454.68
     565 2455.79   574.8 2456.47  579.172457.867   584.7 2459.95   591.2 2461.17
   620.7 2462.48   637.1 2466.16  679.642472.474  730.672477.626   791.1 2481.88
#Mann= 8 ,-1 , 0
       0     .12       0  161.45     .06       0  513.89     .12       0
   550.9    .045       0     565     .06       0  579.17     .12       0
  679.64     .06       0  730.67     .12       0
#XS Ineff= 2 , 0
          355.83 2460.07
Permanent Ineff=
       F       F
Bank Sta=550.9,565
XS Rating Curve= 0 ,0
Exp/Cntr=0.3,0.1

Chan Stop Cuts=-1
Use User Specified Reach Order=0
Composite Channel Slope=5